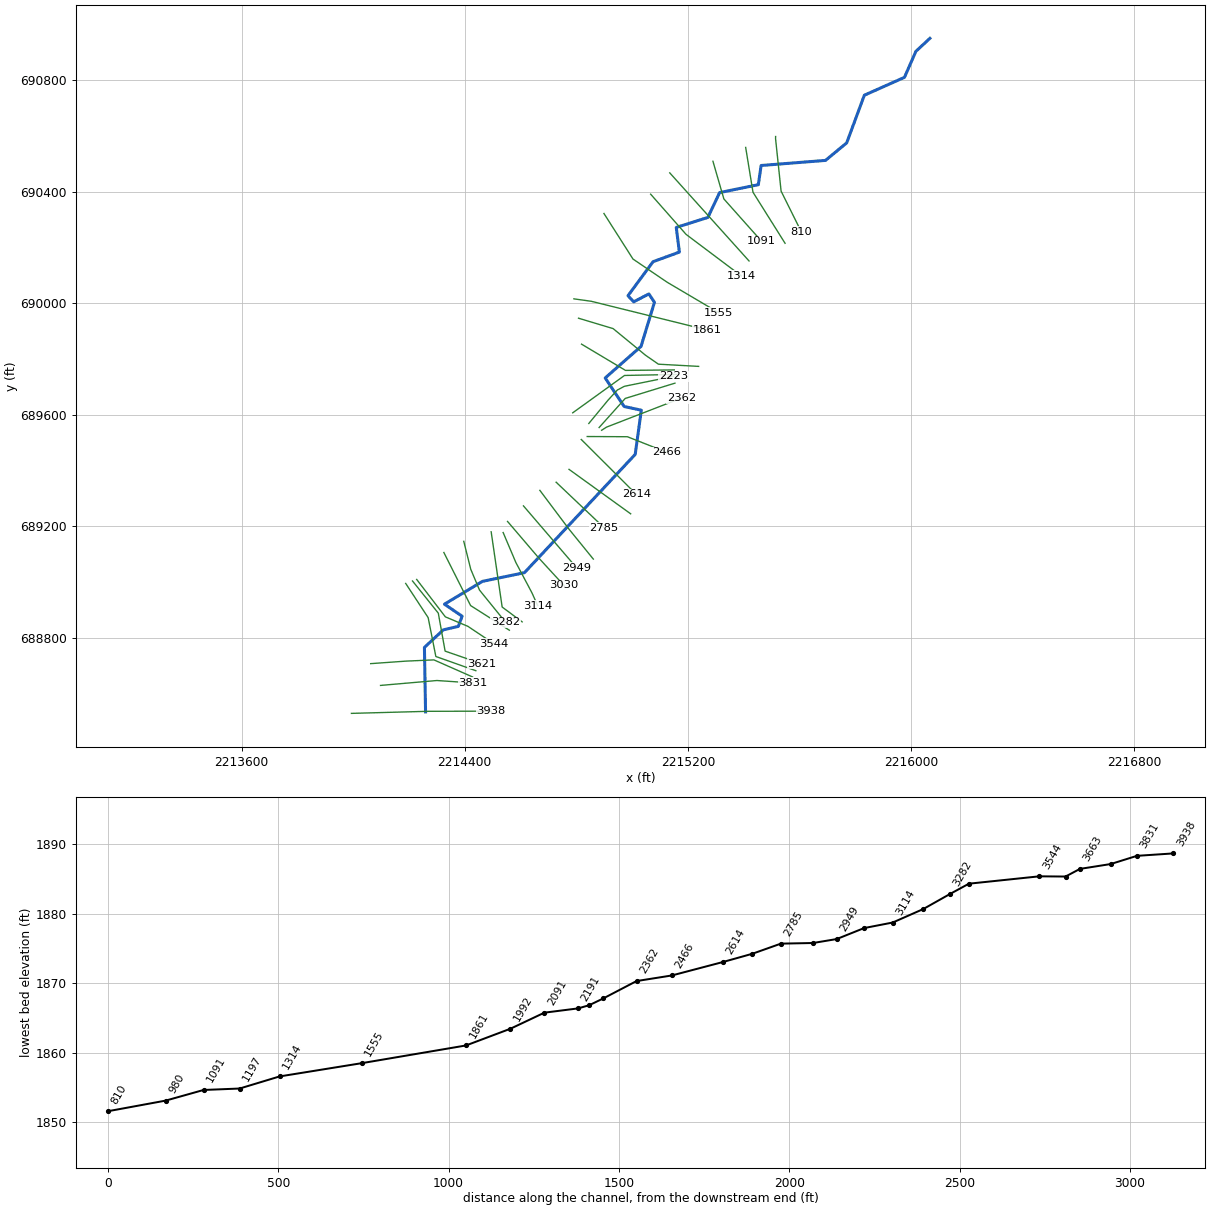
--- LAURELRN4.prj (project) ---

Proj Title=LAURELRN4
Current Plan=p01
Default Exp/Contr=0,0
English Units
Geom File=g01
Flow File=f01
Plan File=p01
BEGIN DESCRIPTION:
---------- MODELED AS PART OF WVEMD CTP PROGRAM, 2023----------
Stream Name: Laurel Run (IV)
Flood Zone:  AFH
Upshur County, WV
HEC-RAS Version: RAS 6.3
Vertical Datum: NAVD88
Projection: NAD 1983 StatePlane West Virginia S FIPS 4702 (US Feet)
Terrain: 1-meter LIDAR (FEMA Region III 3DEP collected 2016-2018)
Land Use: 2019 NLCD
Hydrologic Method:
WV SIR2010-5033 regression equations
Additional Model Notes:
None
END DESCRIPTION:
DSS Export Rating Curves= 0
DSS Export Rating Curve Sorted= 0
DSS Export Volume Flow Curves= 0
DXF OffsetX= 0
DXF OffsetY= 0
DXF ScaleX= 0
DXF ScaleY= 0

--- LAURELRN4.p01 (plan) ---

Plan Title=Floodplain
Program Version=4.00
Geom File=g01
Flow File=f01
K Sum by GR=0
Std Step Tol=0.01
Critical Tol=0.01
Num of Std Step Trials=20
Max Error Tol=0.3
Flow Tol Ratio=0.001
Split Flow NTrial=30
Split Flow Tol=0.02
Split Flow Ratio=0.02
Log Output Level=0
Friction Slope Method=1
Unsteady Friction Slope Method=2
Unsteady Bridges Friction Slope Method=1
Global Log Level=0
CheckData=False
Run HTab=0
Run UNet=0
Run PostProcess=0
UNET Theta=0
UNET Theta Warmup=0
UNET ZTol=0
UNET ZSATol=0
UNET MxIter=0
UNET MaxInSteps=0
UNET DtIC=0
UNET DtMin=0
UNET MaxCRTS=0
UNET WFStab=0
UNET SFStab=0
UNET WFX=0
UNET SFX=0
UNET DSS MLevel=0
UNET DZMax Abort=0
UNET Convert EG Bridges=0
UNET Use Existing IB Tables=0
UNET Froude Limit=0
UNET Froude Power=0
Write IC File=0
Echo Input=False
Echo Output=False
Write Detailed=0

--- LAURELRN4.f01 (steady flow) ---

Flow Title=Flows
Program Version=6.30
Number of Profiles= 1
Profile Names=01pct
River Rch & RM=LAURELRN4,Main            ,3938
     394
River Rch & RM=LAURELRN4,Main            ,1555
     474
Boundary for River Rch & Prof#=LAURELRN4,Main            , 1
Up Type= 0
Dn Type= 3
Dn Slope=0.01748
DSS Import GetInterval= 0
DSS Import GetPeak= 0
DSS Import FillOption= 0

--- LAURELRN4.g01 (geometry) ---

Geom Title=Geometry
Program Version=6.30

River Reach=LAURELRN4       ,Main
Reach XY= 30
     2214259.568      688535.011     2214255.505      688766.231
     2214323.211      688829.159     2214376.981      688841.607
     2214390.517      688878.179     2214327.217      688921.189
     2214463.317      689002.946     2214613.982      689034.052
     2215010.977      689458.061     2215032.955      689616.481
     2214971.487      689629.645     2214903.437      689732.063
     2215031.839      689845.126        2215080.      690003.261
     2215060.083      690033.251      2215005.54       690004.92
     2214985.165      690026.926     2215075.021      690148.775
     2215169.398      690183.172      2215158.18      690271.596
      2215271.53      690307.424     2215313.539       690396.45
     2215452.271      690424.723     2215462.344      690493.574
     2215693.192      690511.831     2215769.026      690574.615
     2215832.325      690745.455     2215976.094      690809.499
     2216017.072      690902.788     2216067.351      690949.347

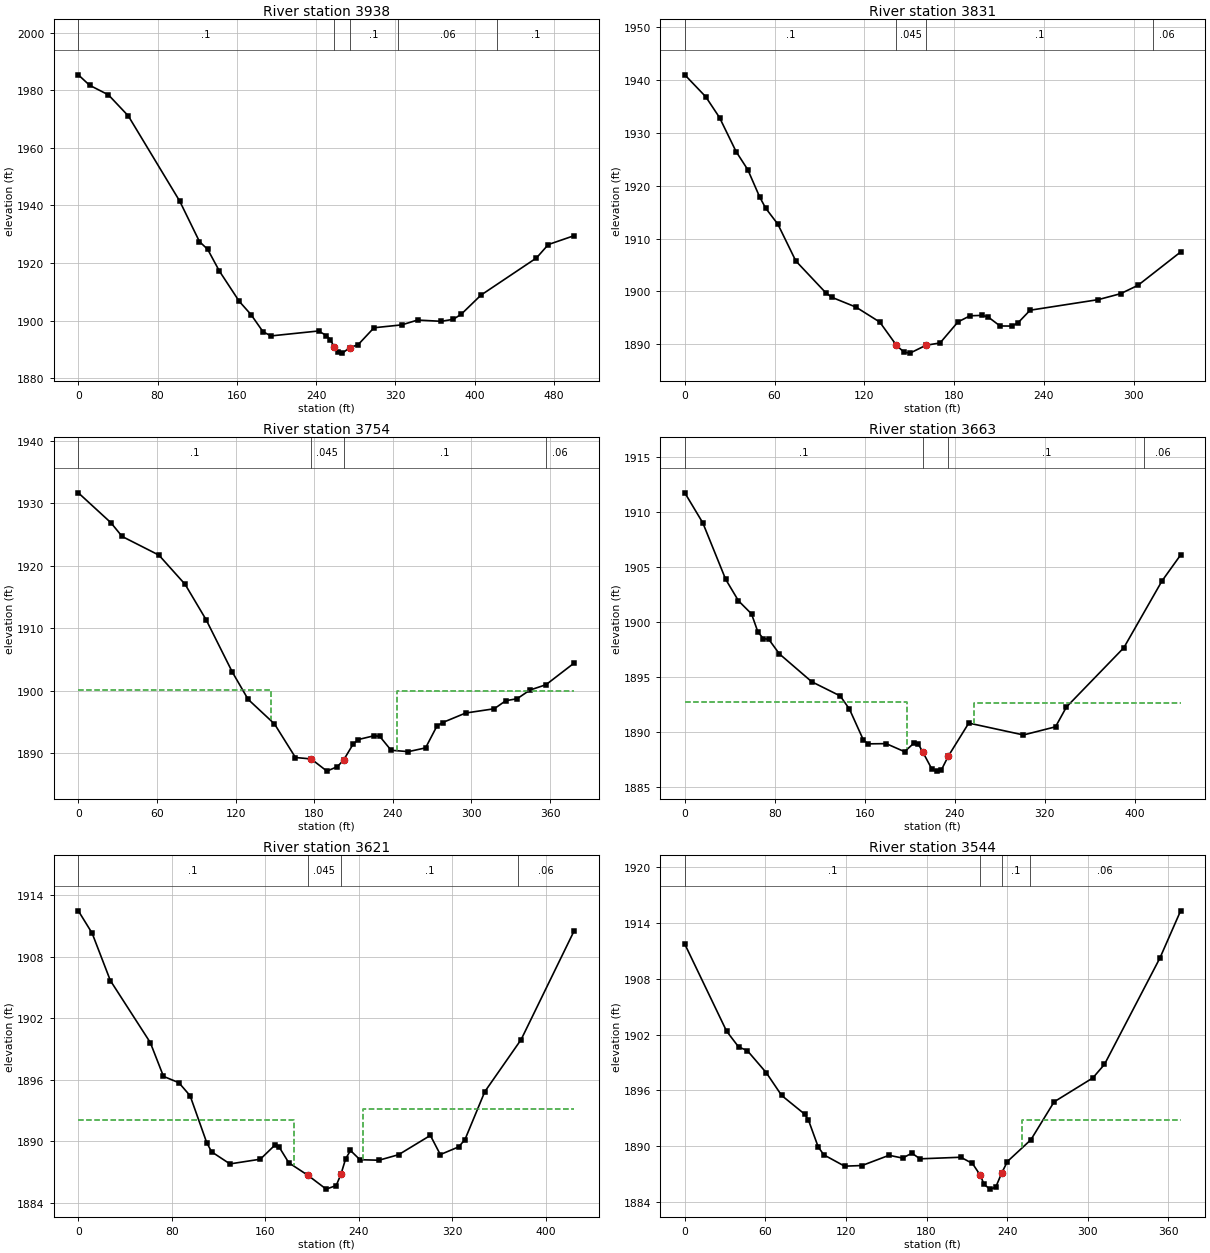
Type RM Length L Ch R = 1 ,3938    ,106.6,107.1,107.5
XS GIS Cut Line= 3
 2213993.8069629688529.8013069092214266.37018075688537.168301179
2214494.32891901688537.718174405
#Sta/Elev= 30
       0 1985.42    11.3 1981.81    30.4 1978.45    50.4 1971.16   102.4 1941.49
   122.3 1927.45   130.6 1924.75   142.4 1917.21   162.4 1906.71   174.4 1902.05
   186.4 1896.14   194.4 1894.66   242.5 1896.38   250.5 1894.78   254.5 1893.34
   258.21890.872   262.5    1889   266.6 1888.68     2741890.588   282.5 1891.62
   298.5  1897.5   326.5  1898.5   342.5 1900.17   366.5 1899.74   378.5 1900.43
   386.5 1902.17   406.5 1908.84   462.5 1921.75   474.5 1926.42   500.6 1929.51
#Mann= 5 ,-1,0
       0      .1       0   258.2    .045       0     274      .1       0
  322.66     .06       0  422.66      .1       0
Bank Sta=258.2,274
XS Rating Curve= 0 ,0
Exp/Cntr=0.3,0.1

Type RM Length L Ch R = 1 ,3831    ,77.4,77,76.6
XS GIS Cut Line= 3
2214098.23844076688629.9973254052214300.55838787688647.590364284
2214428.59661527688638.793844845
#Sta/Elev= 30
       0 1940.99      14 1936.84    23.2 1932.91    34.3 1926.46    42.1 1923.04
    50.1 1917.84    54.1 1915.74    62.2 1912.73    74.2 1905.77    94.3 1899.73
    98.3 1898.89   114.4 1897.04   130.3 1894.21   141.4 1889.84   146.5  1888.5
   150.5 1888.33   161.3 1889.83   170.6 1890.25   182.6 1894.24   190.7  1895.4
   198.7 1895.47   202.7 1895.18   210.7 1893.47   218.7 1893.45   222.7 1894.06
   230.8 1896.45   276.3 1898.45   291.3 1899.58   302.9 1901.16   331.4 1907.47
#Mann= 4 ,-1,0
       0      .1       0   141.4    .045       0   161.3      .1       0
  313.08     .06       0
Bank Sta=141.4,161.3
XS Rating Curve= 0 ,0
Exp/Cntr(USF)=0,0
Exp/Cntr=0.3,0.1

Type RM Length L Ch R = 1 ,3754    ,111.5,90.4,65.1
XS GIS Cut Line= 4
2214062.85602416688708.0510446592214189.39081201688717.066894262
2214289.42834969688721.5557581322214427.92839202688660.427861283
#Sta/Elev= 30
       0 1931.69    24.8 1926.92    33.4 1924.71    61.5 1921.72    81.5 1917.04
    97.6 1911.35   117.6 1902.97   129.6 1898.63   149.7  1894.7   165.7 1889.33
   177.7  1889.1   189.7 1887.15   197.7 1887.87   202.4 1888.91   209.7 1891.46
   213.7 1892.21   225.7 1892.81     230 1892.72   238.7 1890.49   251.9 1890.27
     265 1890.87   273.7 1894.37   278.1 1894.93   295.6 1896.45   317.4 1897.13
   326.2 1898.42   334.9 1898.74   344.6 1900.12   356.9 1900.98   378.4 1904.45
#Mann= 4 ,-1,0
       0      .1       0   177.7    .045       0   202.4      .1       0
  356.99     .06       0
#XS Ineff= 2 , 0
           146.7  1900.2     243            1900
Permanent Ineff=
       F       F
Bank Sta=177.7,202.4
XS Rating Curve= 0 ,0
Exp/Cntr=0.3,0.1

Type RM Length L Ch R = 1 ,3663    ,45.1,42.2,42.6
XS GIS Cut Line= 5
2214188.38743747688995.5028483582214268.89841731688872.918388729
2214278.76750516688823.0535237962214296.42797816688733.712307457
2214439.78946485 688682.80859117
#Sta/Elev= 30
       0 1911.76      16 1909.03    36.3  1903.9    47.7 1901.94    59.3 1900.75
      65  1899.1    69.8  1898.5    74.6 1898.44    84.1 1897.11   112.8 1894.58
   138.1 1893.29   146.3  1892.1   158.6 1889.31   162.7 1888.93     179 1888.95
   195.3 1888.22   203.5 1888.98   207.6  1888.9   211.6 1888.17   219.8  1886.6
   223.9 1886.45   227.9 1886.53   234.3 1887.83   252.4 1890.82     301 1889.74
   329.5 1890.48   339.2 1892.28   390.2 1897.67   424.1 1903.74   440.7 1906.11
#Mann= 4 ,-1,0
       0      .1       0   211.6    .045       0   234.3      .1       0
  408.56     .06       0
#XS Ineff= 2 , 0
          197.75 1892.76  257.46         1892.69
Permanent Ineff=
       F       F
Bank Sta=211.6,234.3
XS Rating Curve= 0 ,0
Exp/Cntr(USF)=0,0
Exp/Cntr=0.3,0.1

Type RM Length L Ch R = 1 ,3621    ,63.5,77.1,90.8
XS GIS Cut Line= 4
2214212.80044426689004.3330848562214305.25821466688889.020584697
2214329.67122145688752.931057483 2214460.5664982688707.725844794
#Sta/Elev= 30
       0  1912.5    11.8 1910.32    27.4  1905.7    61.6 1899.65    72.9 1896.35
    86.1 1895.73    95.7 1894.46   109.9 1889.89   114.1 1888.99   129.8 1887.81
   155.8 1888.27     168 1889.61     172 1889.44   180.2 1887.92   196.4 1886.71
   212.2 1885.35   220.8  1885.7   224.9 1886.83   228.9 1888.32     233 1889.12
   241.1 1888.22   257.4 1888.17   274.2 1888.71   301.4 1890.59   309.9 1888.72
   325.6 1889.47     331 1890.18     348 1894.86   379.1 1899.94   424.5 1910.55
#Mann= 4 ,-1,0
       0      .1       0   196.4    .045       0   224.9      .1       0
  376.06     .06       0
#XS Ineff= 2 , 0
          184.51 1892.05  243.94         1893.18
Permanent Ineff=
       F       F
Bank Sta=196.4,224.9
XS Rating Curve= 0 ,0
Exp/Cntr=0.3,0.1

Type RM Length L Ch R = 1 ,3544    ,219.2,206.6,182.4
XS GIS Cut Line= 4
 2214227.7609939689009.8985257742214330.60221823688875.722678179
2214411.40176789 688841.73556602 2214504.9401489688779.293783057
#Sta/Elev= 30
       0 1911.74    31.1 1902.38    40.1 1900.67    46.5 1900.29    60.7  1897.9
    72.1 1895.46    89.3 1893.44    92.1  1892.8    99.3 1889.93   103.5 1889.07
     119 1887.85     132 1887.92   152.1 1889.02   162.2 1888.72   169.1 1889.25
   175.1 1888.64   205.5 1888.81   214.2 1888.14   220.11886.856   222.8  1885.9
   227.2 1885.38   231.5 1885.58   235.9 1887.09   240.2 1888.35   257.7 1890.69
     275 1894.77   303.8 1897.34   312.5  1898.8   353.8 1910.25   369.2 1915.32
#Mann= 4 ,-1,0
       0      .1       0   220.1    .045       0   235.9      .1       0
  256.71     .06       0
#XS Ineff= 2 , 0
                          251.04         1892.83
Permanent Ineff=
       F       F
Bank Sta=220.1,235.9
XS Rating Curve= 0 ,0
Exp/Cntr(USF)=0,0
Exp/Cntr=0.3,0.1

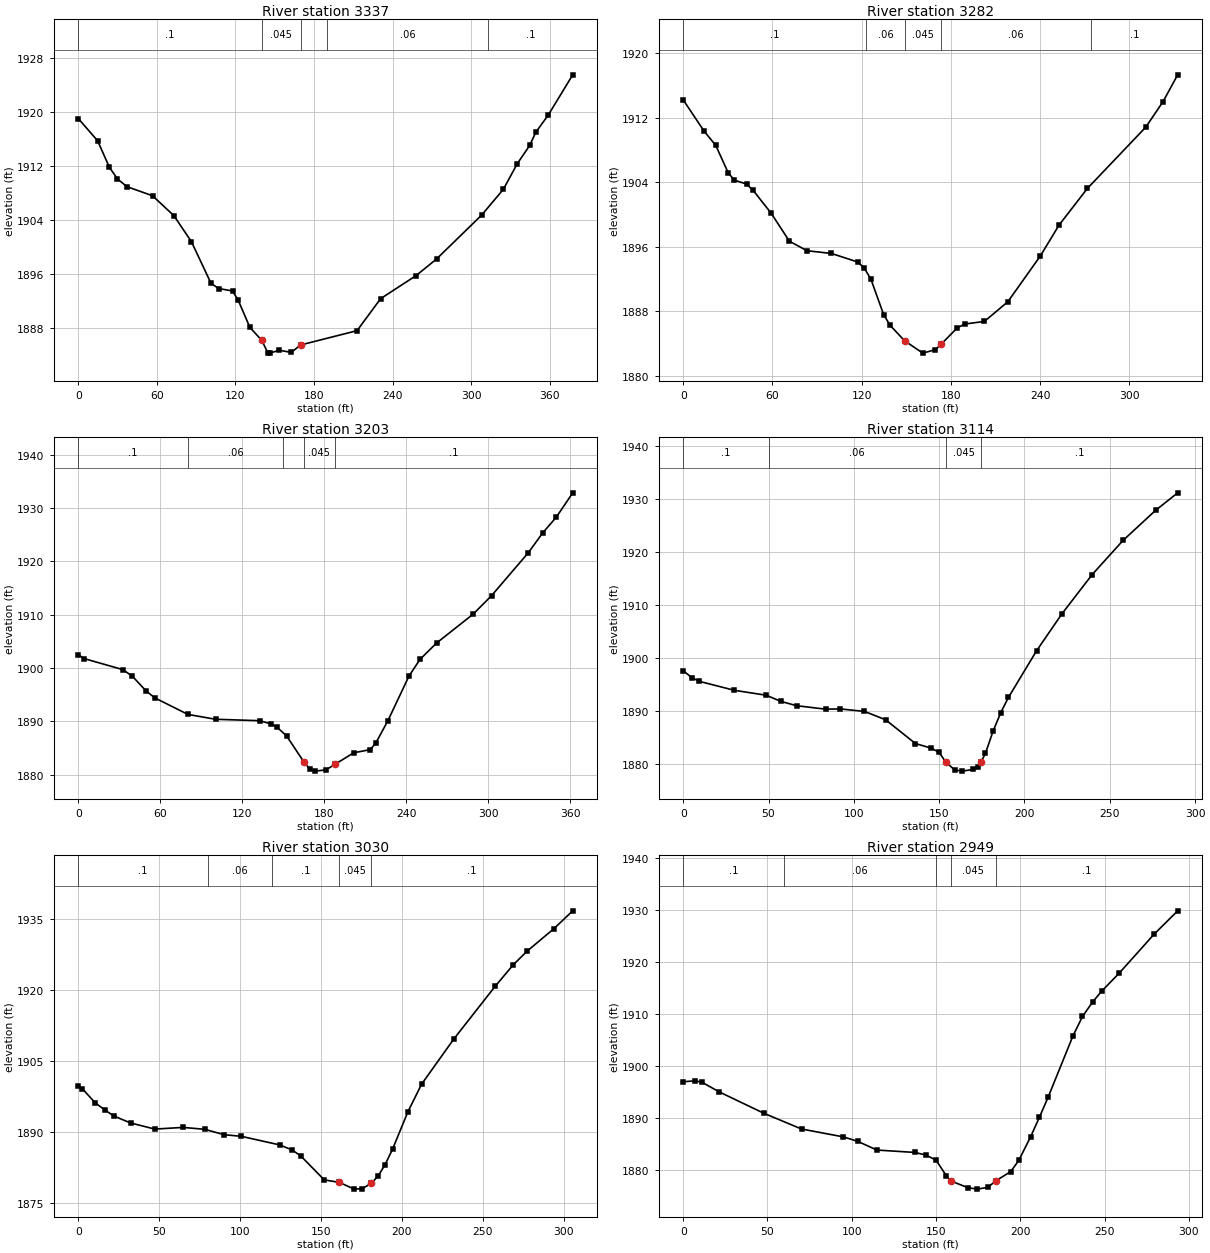
Type RM Length L Ch R = 1 ,3337    ,56.3,55.1,54
XS GIS Cut Line= 3
2214325.22266191 689106.375757952214421.01623082688916.213832218
2214559.95725537688827.861590967
#Sta/Elev= 30
       0 1918.99    14.8  1915.7    23.7 1911.81    29.9 1910.07    37.2 1908.92
    56.7 1907.58      73 1904.64    86.4  1900.8   101.4 1894.63   107.3 1893.86
   117.8 1893.51   122.2 1892.12     131 1888.14   140.2 1886.19   144.7 1884.39
   146.1 1884.32   153.6 1884.74   162.6 1884.43   169.9 1885.53   212.9 1887.64
   230.9 1892.37     258 1895.78   273.6 1898.23     308 1904.71   324.6 1908.52
   335.2  1912.3   344.7 1915.01   349.4 1916.96   358.9  1919.5   377.6 1925.45
#Mann= 5 ,-1,0
       0      .1       0   140.2    .045       0   169.9      .1       0
     190     .06       0  312.93      .1       0
Bank Sta=140.2,169.9
XS Rating Curve= 0 ,0
Exp/Cntr=0.3,0.1

Type RM Length L Ch R = 1 ,3282    ,83,78.9,74.6
XS GIS Cut Line= 4
2214396.52400694689146.4599321612214421.50177819689046.548847167
2214452.99548976688971.6155334212214546.39063443688856.500587668
#Sta/Elev= 30
       0 1914.18      14 1910.32    21.9 1908.54    30.2 1905.18    34.3 1904.26
    42.6 1903.76    46.9 1903.01      59 1900.19    71.4  1896.7    83.2 1895.52
    99.7 1895.18   117.5 1894.11   121.8 1893.35   126.2    1892   134.8  1887.6
   139.2 1886.27   148.8 1884.39   161.1 1882.85   169.6 1883.28   173.3 1883.93
   184.3 1885.98   189.3 1886.45   202.5 1886.77   218.3 1889.21   240.1 1894.86
   252.8 1898.71   271.8 1903.23     311  1910.8   322.6 1913.95   332.5 1917.28
#Mann= 5 ,-1,0
       0      .1       0  122.99     .06       0   148.8    .045       0
   173.3     .06       0  274.27      .1       0
Bank Sta=148.8,173.3
XS Rating Curve= 0 ,0
Exp/Cntr(USF)=0,0
Exp/Cntr=0.3,0.1

Type RM Length L Ch R = 1 ,3203    ,83.7,89.6,94.3
XS GIS Cut Line= 3
2214494.74603301 689180.55992752 2214534.1081943688910.954599583
2214605.78353788688857.741086924
#Sta/Elev= 30
       0 1902.49     4.2 1901.77    32.5  1899.7    39.5 1898.48    49.6  1895.7
      56  1894.4    80.2  1891.3   100.4 1890.39   132.8 1890.12   140.9 1889.53
   145.3 1888.93   152.4 1887.26   165.1 1882.37   169.2 1881.12   173.2 1880.67
   181.3 1880.91   187.7 1881.93   201.5 1884.11   213.6  1884.7   217.7 1885.97
   226.5 1890.12   241.9 1898.48     250 1901.62   262.1 1904.68   288.9  1910.1
   302.3 1913.55   329.1 1921.57   339.8 1925.34   349.8  1928.3   361.7 1932.83
#Mann= 5 ,-1,0
       0      .1       0      80     .06       0     150      .1       0
   165.1    .045       0   187.7      .1       0
Bank Sta=165.1,187.7
XS Rating Curve= 0 ,0
Exp/Cntr=0.3,0.1

Type RM Length L Ch R = 1 ,3114    ,80.5,84.1,87.8
XS GIS Cut Line= 4
  2214537.702714689177.9536437352214583.31429628689070.440628361
2214640.87176915688961.8416229332214661.50558018688916.230040653
#Sta/Elev= 30
       0 1897.67     5.2 1896.33     9.5 1895.66    29.9 1893.98    48.6 1893.05
    57.3 1891.88    66.5 1891.07    83.4 1890.42    92.1 1890.46   106.2    1890
   118.6 1888.42   136.1 1883.93   145.4 1883.06   149.9 1882.28   153.9 1880.46
     159 1878.96   163.5 1878.73   169.9 1879.04   172.5 1879.54   174.6 1880.53
   177.1 1882.06   181.6 1886.27   186.1 1889.76   190.6 1892.63   207.1 1901.44
   221.9 1908.38   239.7 1915.82   257.8 1922.26   276.8 1927.91   289.8 1931.23
#Mann= 4 ,-1,0
       0      .1       0      50     .06       0   153.9    .045       0
   174.6      .1       0
Bank Sta=153.9,174.6
XS Rating Curve= 0 ,0
Exp/Cntr(USF)=0,0
Exp/Cntr=0.3,0.1

Type RM Length L Ch R = 1 ,3030    ,80.3,80.3,79.6
XS GIS Cut Line= 3
2214553.42795737689217.768509716     2214666.247      689085.744
2214755.42210746688988.624608265
#Sta/Elev= 30
       0 1899.62     2.4 1899.17    10.4 1896.18    16.6 1894.59    22.2 1893.34
    32.3  1891.9    47.3 1890.61    64.8 1890.96    78.1 1890.56    90.2 1889.42
   100.7 1889.08   124.4 1887.27   132.3 1886.17   137.6  1884.9     152 1879.87
   161.2 1879.37   170.5 1877.93   175.4 1878.03   181.1 1879.17   185.3 1880.72
   189.6 1883.11   194.3 1886.46   203.7 1894.29   212.2 1900.13     232 1909.61
   257.5 1920.72   268.8 1925.31   277.3 1928.17   293.9 1932.93   305.5 1936.69
#Mann= 5 ,-1,0
       0      .1       0      80     .06       0     120      .1       0
   161.2    .045       0   181.1      .1       0
Bank Sta=161.2,181.1
XS Rating Curve= 0 ,0
Exp/Cntr=0.3,0.1

Type RM Length L Ch R = 1 ,2949    ,70.8,69.7,69.7
XS GIS Cut Line= 2
2214610.46404763689273.5207685112214801.59829719689050.892807384
#Sta/Elev= 30
       0 1897.02     7.1 1897.19      11 1896.94    21.5 1895.04    47.9 1890.94
    70.2 1887.92    95.1  1886.4   103.6 1885.54   114.9 1883.87   137.5 1883.41
   143.9 1882.91     150 1881.94   156.1 1878.93   158.6 1877.95   168.8 1876.64
   174.4 1876.35   180.7 1876.69   185.8 1878.01   194.3 1879.72   199.1 1881.87
   206.1  1886.4   211.4 1890.22   216.6 1894.11   231.2 1905.79   236.9 1909.58
     243  1912.4   248.2 1914.41   258.8 1917.95   279.4 1925.41   293.4 1929.91
#Mann= 5 ,-1,0
       0      .1       0      60     .06       0     150      .1       0
   158.6    .045       0   185.8      .1       0
Bank Sta=158.6,185.8
XS Rating Curve= 0 ,0
Exp/Cntr(USF)=0,0
Exp/Cntr=0.3,0.1

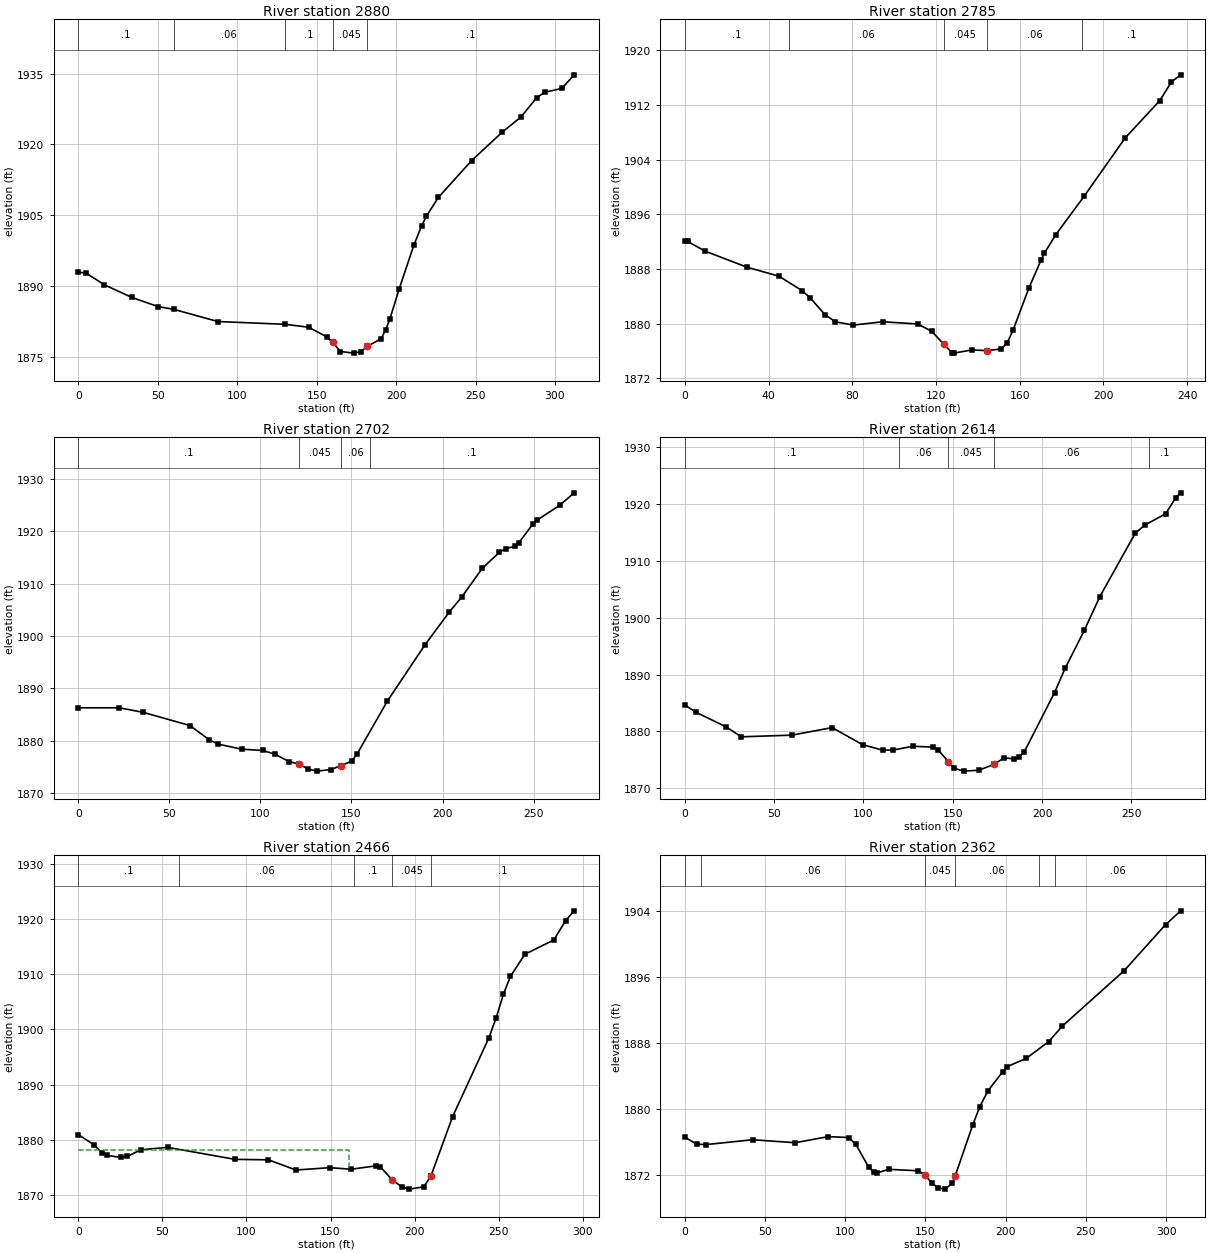
Type RM Length L Ch R = 1 ,2880    ,90.1,94.3,95
XS GIS Cut Line= 3
2214669.26423158689329.160990022     2214773.201      689190.727
2214860.83287716689082.858445713
#Sta/Elev= 30
       0 1892.94       5 1892.71    16.4 1890.25    33.5  1887.6      50 1885.65
      60 1885.06    87.8 1882.47     130 1881.89     145 1881.26   156.3 1879.24
     160  1878.1     165 1876.12   173.5 1875.78   177.8 1876.11     182 1877.25
   190.6 1878.82   193.4 1880.67   196.2  1883.1   201.9 1889.33   211.2 1898.65
   216.1 1902.76     219 1904.72   226.6 1908.75   247.6 1916.57   266.6 1922.51
   278.7 1925.82   288.5 1929.88   293.6 1931.02   304.3 1931.84   312.1 1934.72
#Mann= 5 ,-1,0
       0      .1       0      60     .06       0     130      .1       0
     160    .045       0     182      .1       0
Bank Sta=160,182
XS Rating Curve= 0 ,0
Exp/Cntr=0.3,0.1

Type RM Length L Ch R = 1 ,2785    ,81.6,83.8,86.1
XS GIS Cut Line= 2
2214727.56210223689358.4004521082214899.35812689689195.312981697
#Sta/Elev= 30
       0 1892.06     1.3 1892.04     9.8 1890.61    29.6 1888.28      45 1886.95
      56 1884.85    59.9 1883.78      67 1881.31      72 1880.27    80.5  1879.8
    94.6 1880.28   111.2 1879.96     118 1878.89   123.8 1876.97   127.7 1875.76
   128.6 1875.69   137.1 1876.16   144.2 1876.06   151.3  1876.3   154.1  1877.2
   156.9 1879.11   164.4 1885.21   170.3 1889.37   171.8 1890.32   177.3 1893.05
   190.9  1898.7   210.4 1907.19     227 1912.67   232.5 1915.39   236.9 1916.43
#Mann= 5 ,-1,0
       0      .1       0      50     .06       0   123.8    .045       0
   144.2     .06       0     190      .1       0
Bank Sta=123.8,144.2
XS Rating Curve= 0 ,0
Exp/Cntr(USF)=0,0
Exp/Cntr=0.3,0.1

Type RM Length L Ch R = 1 ,2702    ,90.2,87.3,84.6
XS GIS Cut Line= 2
2214773.84507381689404.4201007832214994.73545085689245.105359821
#Sta/Elev= 30
       0 1886.32    22.6 1886.31    35.5 1885.46    61.3 1882.93    71.9 1880.21
    76.9 1879.37    89.9 1878.41   101.3 1878.17   108.1 1877.44   115.7 1876.06
   121.2 1875.57   126.2 1874.63   131.1 1874.23   138.7 1874.53   144.4  1875.3
   150.1 1876.14     153 1877.46   169.7 1887.58   190.3  1898.3   203.8 1904.63
   210.7 1907.52   221.8 1912.91   231.2 1915.99   234.7  1916.7   239.6 1917.13
   241.8 1917.75   249.5 1921.33   251.7 1922.09   264.3 1924.94   272.3 1927.34
#Mann= 4 ,-1,0
       0      .1       0   121.2    .045       0   144.4     .06       0
     160      .1       0
Bank Sta=121.2,144.4
XS Rating Curve= 0 ,0
Exp/Cntr=0.3,0.1

Type RM Length L Ch R = 1 ,2614    ,143.4,148.7,156.6
XS GIS Cut Line= 2
2214817.73851718689511.4359623762215014.39350577689315.493491859
#Sta/Elev= 30
       0 1884.65     6.1  1883.4    23.1 1880.81    31.7 1879.06    59.9 1879.35
    82.5 1880.68    99.5 1877.68   110.7 1876.72   116.4 1876.72   127.7  1877.4
   139.1 1877.25   141.9 1876.73   147.6 1874.68   150.5 1873.57   156.1 1873.03
   164.5 1873.18   173.2 1874.22   178.7 1875.36   184.5 1875.19   187.2 1875.54
     190 1876.38     207 1886.82   212.9 1891.07   223.7 1897.78   232.4 1903.71
   252.2 1914.83   257.5 1916.26   269.2 1918.25   274.8 1921.03   277.6 1921.93
#Mann= 5 ,-1,0
       0      .1       0     120     .06       0   147.6    .045       0
   173.2     .06       0     260      .1       0
Bank Sta=147.6,173.2
XS Rating Curve= 0 ,0
Exp/Cntr(USF)=0,0
Exp/Cntr=0.3,0.1

Type RM Length L Ch R = 1 ,2466    ,93.9,103.9,116.8
XS GIS Cut Line= 3
2214839.11405942689522.1237334952214983.04271049689521.411215421
2215123.40877118689465.834805601
#Sta/Elev= 30
       0 1880.98     9.1 1879.17    13.9 1877.73    17.1 1877.21    25.1 1876.86
    29.1 1877.02    37.1 1878.22    53.1 1878.67    93.1  1876.5   113.1 1876.41
   129.4 1874.57   149.5 1874.99   162.4 1874.71   177.2 1875.33   179.6 1875.14
   186.6 1872.83   192.5 1871.47   196.8 1871.11   205.4 1871.52   209.7 1873.46
   209.7 1873.48   222.6 1884.22   244.1 1898.43   248.4    1902   252.8 1906.36
     257 1909.61   265.6 1913.61   282.8 1916.19   289.8  1919.7   294.9 1921.47
#Mann= 5 ,-1,0
       0      .1       0      60     .06       0  163.93      .1       0
   186.6    .045       0   209.7      .1       0
#XS Ineff= 2 , 0
          160.73 1878.14
Permanent Ineff=
       F       F
Bank Sta=186.6,209.7
XS Rating Curve= 0 ,0
Exp/Cntr(USF)=0,0
Exp/Cntr=0.3,0.1

Type RM Length L Ch R = 1 ,2362    ,88.7,97.2,101.1
XS GIS Cut Line= 3
2214890.65580644689544.5917671752214908.31553183689555.886947188
2215176.93484596689659.914586081
#Sta/Elev= 30
       0 1876.61     7.3 1875.76    13.1  1875.7    42.3 1876.29    68.8 1875.93
    89.4 1876.67   102.2 1876.56   106.6 1875.72   114.6 1872.96   117.7  1872.4
   119.5 1872.24     127  1872.7   145.2 1872.53   149.5 1872.06   153.8 1871.06
   157.9 1870.45   162.4  1870.3   166.7 1871.03   168.5  1871.9   179.5 1878.12
   183.8 1880.28   188.8 1882.19   198.1 1884.54     201 1885.17   212.8 1886.16
   226.7 1888.18   235.3 1890.08   273.9 1896.82   299.6 1902.38     309 1904.06
#Mann= 6 ,-1,0
       0      .1       0      10     .06       0   149.5    .045       0
   168.5     .06       0  220.96      .1       0  230.96     .06       0
Bank Sta=149.5,168.5
XS Rating Curve= 0 ,0
Exp/Cntr=0.3,0.1

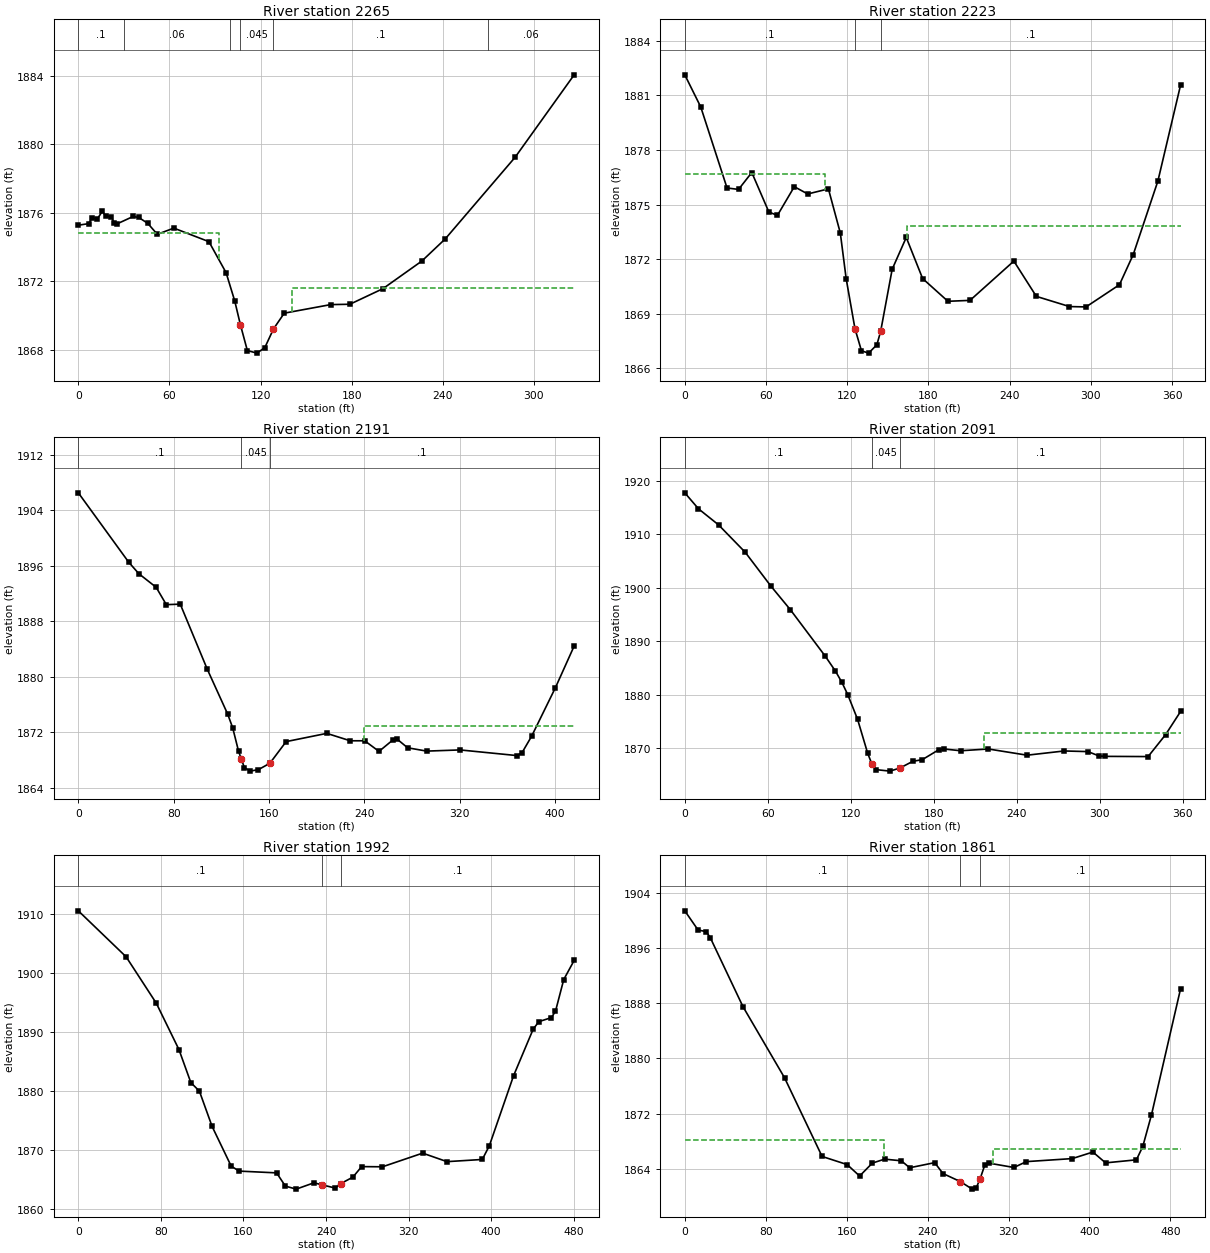
Type RM Length L Ch R = 1 ,2265    ,41.8,41.5,41.3
XS GIS Cut Line= 3
2214881.62774696689554.3329595182214975.14608983689658.598863552
2215153.33827943689713.370713114
#Sta/Elev= 30
       0 1875.27     6.7 1875.36     9.2 1875.71    12.3 1875.61    15.8 1876.08
      18 1875.81    21.8 1875.75    23.6  1875.4    25.3 1875.34    36.1 1875.78
    39.8 1875.72    45.7 1875.38      52 1874.74    62.9  1875.1      86 1874.31
    97.3  1872.5     103 1870.85   106.71869.473   111.3 1867.96   117.6 1867.81
   122.8 1868.13   128.5 1869.22   135.6 1870.14   166.2 1870.64   178.8 1870.66
   200.6 1871.57   226.2 1873.18   241.6 1874.47   287.6 1879.23   326.5 1884.04
#Mann= 6 ,-1,0
       0      .1       0      30     .06       0     100      .1       0
   106.7    .045       0   128.5      .1       0  270.06     .06       0
#XS Ineff= 2 , 0
           92.48 1874.84  140.59         1871.63
Permanent Ineff=
       F       F
Bank Sta=106.7,128.5
XS Rating Curve= 0 ,0
Exp/Cntr=0.3,0.1

Type RM Length L Ch R = 1 ,2223    ,36.1,32.3,29.2
XS GIS Cut Line= 5
2214844.68997775689568.7864983892214913.09937818689651.787604922
2214946.86204715689688.6668279452214972.31390529689702.171895532
2215148.68777941689737.954553238
#Sta/Elev= 30
       0 1882.13    11.8 1880.36    31.2 1875.91    39.7 1875.83    49.5 1876.76
    62.1 1874.59    68.4  1874.4    80.9 1875.98    90.8 1875.58   106.1 1875.86
   114.9 1873.43   119.2 1870.93   125.7 1868.18   130.5 1866.96   135.8 1866.83
   141.9 1867.29   144.7 1868.03   153.2 1871.44   163.6 1873.19   175.7 1870.93
   194.4 1869.68   210.7 1869.73   243.1 1871.89   259.7 1869.95   284.2 1869.39
   296.4 1869.37   321.1 1870.59   331.3 1872.25   349.5 1876.29   366.3 1881.58
#Mann= 3 ,-1,0
       0      .1       0   125.7    .045       0   144.7      .1       0
#XS Ineff= 2 , 0
          103.66  1876.7  164.06          1873.8
Permanent Ineff=
       F       F
Bank Sta=125.7,144.7
XS Rating Curve= 0 ,0
Exp/Cntr(USF)=0,0
Exp/Cntr=0.3,0.1

Type RM Length L Ch R = 1 ,2191    ,121.7,99.5,83.1
XS GIS Cut Line= 3
2214787.18745915 689607.188248562214972.68175675689740.993891251
2215159.83441217689744.704236959
#Sta/Elev= 30
       0 1906.54    42.2 1896.54    50.8 1894.86    65.3  1892.9    73.8  1890.4
    85.5 1890.47   108.1  1881.1   125.3 1874.59   129.5 1872.61   134.4 1869.24
   136.8 1868.06   139.3 1866.88   144.2 1866.37   151.1 1866.59   160.7 1867.51
   174.3 1870.63   208.4 1871.82   228.1 1870.75   240.2 1870.75   252.2 1869.22
   264.2 1870.92   267.6 1870.96   276.2 1869.74   292.2 1869.26   320.2 1869.43
   368.2 1868.61   372.2 1869.04   380.2  1871.4   400.2 1878.42   415.9 1884.43
#Mann= 3 ,-1,0
       0      .1       0   136.8    .045       0   160.7      .1       0
#XS Ineff= 2 , 0
                             240         1872.88
Permanent Ineff=
       F       F
Bank Sta=136.8,160.7
XS Rating Curve= 0 ,0
Exp/Cntr=0.3,0.1

Type RM Length L Ch R = 1 ,2091    ,100.3,99.6,95.3
XS GIS Cut Line= 3
2214818.68042652689853.2001289752214976.23954836689759.126367585
2215151.11285941689760.857786506
#Sta/Elev= 30
       0 1917.78     9.9 1914.79    24.4 1911.79    43.7 1906.66    62.3 1900.32
    76.3 1895.93   101.5 1887.25   108.9 1884.45   113.6 1882.32   117.8 1880.04
   124.9 1875.43   132.2 1869.08   135.3 1867.04   138.2 1866.03   148.3 1865.75
   155.5 1866.33   164.8 1867.58   171.7  1867.9   183.4 1869.72   187.4 1869.89
   199.4 1869.56   219.4 1869.89   247.4 1868.73   274.3 1869.52   291.4  1869.4
   299.4 1868.59   303.4 1868.51   334.9 1868.47   347.5 1872.56   358.4 1876.91
#Mann= 3 ,-1,0
       0      .1       0   135.3    .045       0   155.5      .1       0
#XS Ineff= 2 , 0
                          216.11         1872.81
Permanent Ineff=
       F       F
Bank Sta=135.3,155.5
XS Rating Curve= 0 ,0
Exp/Cntr(USF)=0,0
Exp/Cntr=0.3,0.1

Type RM Length L Ch R = 1 ,1992    ,122.4,130.5,135.3
XS GIS Cut Line= 5
2214807.80766573 689946.207607682214931.93437415689908.916229603
2215048.07482031689813.4388076062215094.38849516689781.375494249
2215238.31714623689773.537795428
#Sta/Elev= 30
       0 1910.53    46.3 1902.75    75.6 1894.88    97.5 1887.05     109 1881.47
   117.3 1880.02   129.6 1874.05   148.1 1867.33   155.8 1866.49   192.1 1866.19
   200.6 1863.95   211.1 1863.44   228.3 1864.51   236.3 1864.16   248.9 1863.62
   254.2 1864.37     266 1865.47   274.5 1867.25   294.7 1867.22   333.6 1869.53
   357.2 1868.09   391.4 1868.46   398.2 1870.77   421.7 1882.63   440.7 1890.51
   446.2 1891.78   458.3 1892.46   462.3 1893.53   470.3  1898.9   480.4 1902.14
#Mann= 3 ,-1,0
       0      .1       0   236.3    .045       0   254.2      .1       0
Bank Sta=236.3,254.2
XS Rating Curve= 0 ,0
Exp/Cntr=0.3,0.1

Type RM Length L Ch R = 1 ,1861    ,305.1,306,295.9
XS GIS Cut Line= 3
 2214791.1920179690015.6023721482214853.74504502690006.805852709
2215268.15884973 689904.17979258
#Sta/Elev= 30
       0  1901.4    13.1 1898.62    21.2 1898.38    25.2  1897.5    57.5  1887.5
    98.6 1877.18   135.7 1865.77   160.5 1864.59   172.8 1862.93   185.4 1864.81
   197.5 1865.38     214 1865.14   222.3 1864.13     247 1864.87   255.2 1863.29
   272.4 1862.12   284.1 1861.03   288.2 1861.26   291.8 1862.49   296.4 1864.46
     301 1864.79   325.3 1864.17   337.6 1865.02     383 1865.46   403.4 1866.41
   415.9 1864.84   446.4 1865.28   452.7 1867.22   461.3 1871.81   490.1 1890.13
#Mann= 3 ,-1,0
       0      .1       0   272.4    .045       0   291.8      .1       0
#XS Ineff= 2 , 0
           196.9  1868.1  304.51         1866.78
Permanent Ineff=
       F       F
Bank Sta=272.4,291.8
XS Rating Curve= 0 ,0
Exp/Cntr=0.3,0.1

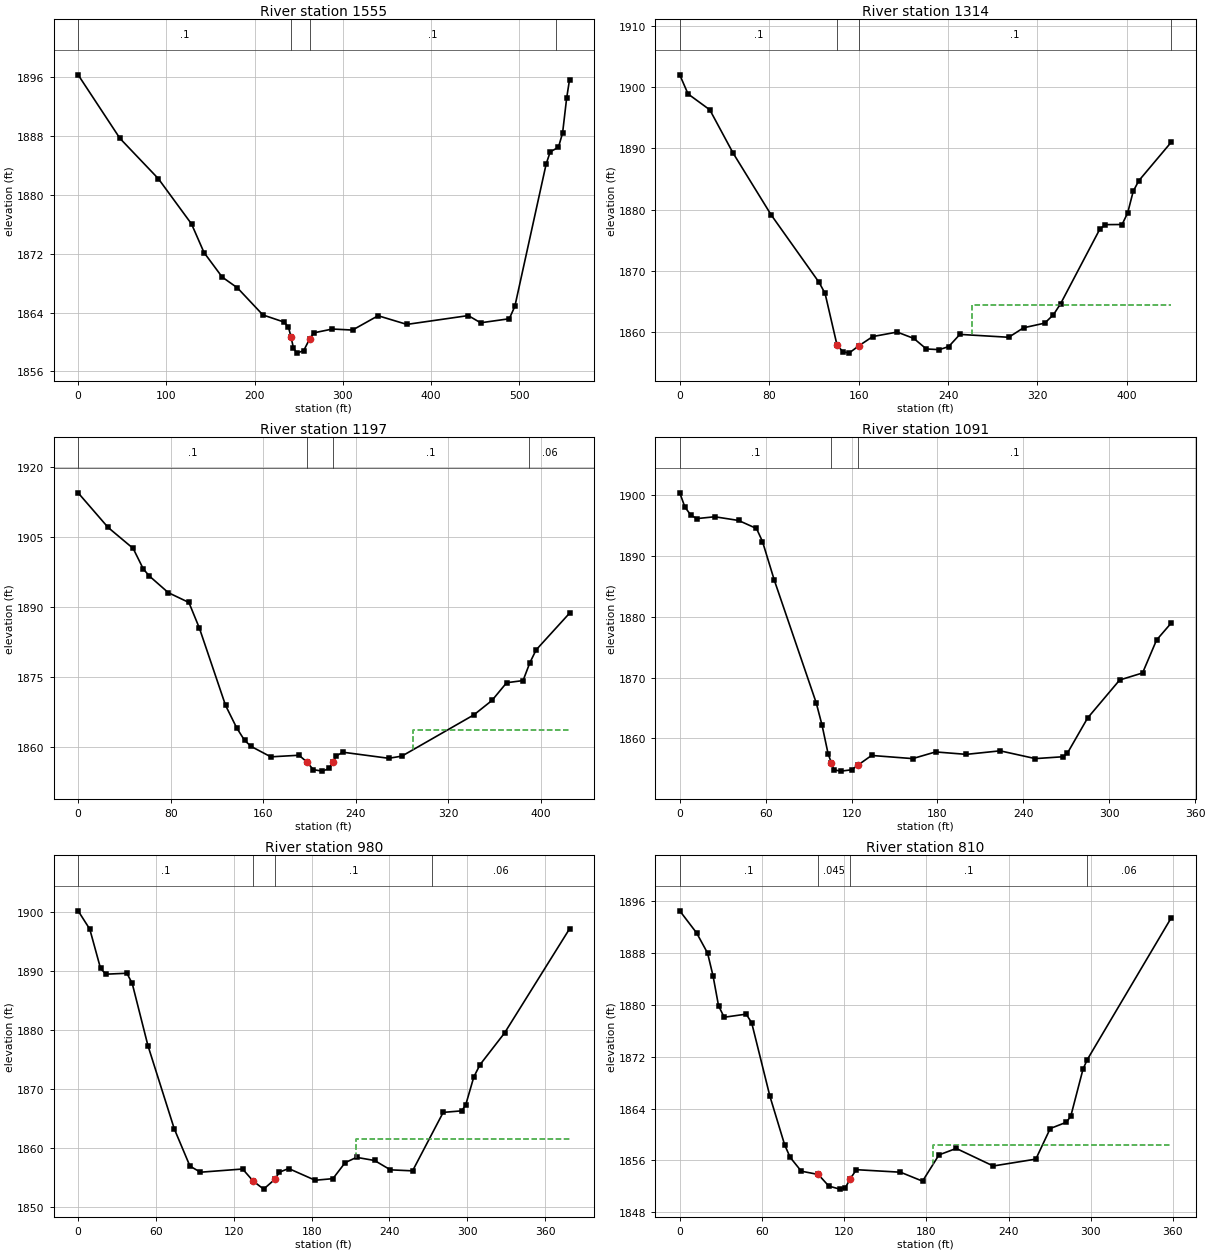
Type RM Length L Ch R = 1 ,1555    ,242.2,241.2,235
XS GIS Cut Line= 4
2214899.02312098690321.5399752742215003.04533453690158.294837416
2215125.61168783690075.0751840512215310.96705851689965.667984826
#Sta/Elev= 30
       0 1896.36    47.4 1887.71    90.9 1882.23   128.6 1876.05   142.7 1872.17
   163.3 1868.83   180.5 1867.37   209.4 1863.68   233.6  1862.7   238.4    1862
   241.3  1860.7   244.1 1859.14   248.1 1858.48   255.7 1858.83   262.6 1860.45
   267.2 1861.24   288.1 1861.76     311 1861.62     340 1863.57   372.6 1862.39
   442.2 1863.59   456.2 1862.61   488.7 1863.16     495 1864.85   530.5 1884.23
   535.1 1885.88   544.4  1886.5   549.1 1888.44   553.7 1893.18     557 1895.72
#Mann= 4 ,-1,0
       0      .1       0   241.3    .045       0   262.6      .1       0
  541.72     .06       0
Bank Sta=241.3,262.6
XS Rating Curve= 0 ,0
Exp/Cntr=0.3,0.1

Type RM Length L Ch R = 1 ,1314    ,115.3,117.2,116.9
XS GIS Cut Line= 4
2215066.39058679690390.7392615312215193.21880407690246.810610461
2215245.23262352690207.6221163582215391.29882881690097.894332869
#Sta/Elev= 30
       0 1902.03     7.4 1898.91    26.9 1896.31    47.7 1889.25    81.7 1879.17
   124.7 1868.11     130 1866.32   140.7 1857.88     146  1856.8   151.4 1856.57
     160 1857.74   172.7 1859.28   194.5 1860.01   209.4 1858.97   220.6 1857.25
   232.2 1857.14   240.6 1857.64   250.6 1859.63   294.3 1859.16   307.6 1860.71
   326.5 1861.47   334.3 1862.84   340.8 1864.67   375.7 1876.79   380.7 1877.56
   395.7 1877.58   400.7 1879.47   405.7 1883.02   410.7 1884.74   439.6 1891.01
#Mann= 4 ,-1,0
       0      .1       0   140.7    .045       0     160      .1       0
  439.65     .06       0
#XS Ineff= 2 , 0
                          261.41          1864.4
Permanent Ineff=
       F       F
Bank Sta=140.7,160
XS Rating Curve= 0 ,0
Exp/Cntr=0.3,0.1

Type RM Length L Ch R = 1 ,1197    ,110.3,106,99.5
XS GIS Cut Line= 2
2215134.88036467 690467.130433172215419.08703372690151.333188464
#Sta/Elev= 30
       0 1914.42    25.9 1907.01    47.6 1902.51    56.4  1898.1    61.7 1896.58
      78 1893.04    95.8 1890.94   104.9 1885.42   127.5 1868.89   137.2 1864.05
   143.9 1861.43   149.6 1860.12   166.6 1857.89     191 1858.23   197.7 1856.81
   203.4 1855.14   211.2 1854.83   217.2 1855.41   220.4 1856.87   223.2 1858.09
   228.9 1858.88   268.5 1857.58   279.9 1858.04   342.2 1866.88   357.8 1869.96
   370.5 1873.76   384.7 1874.22   390.6 1878.05     396 1880.79   424.9 1888.65
#Mann= 4 ,-1,0
       0      .1       0   197.7    .045       0   220.4      .1       0
     390     .06       0
#XS Ineff= 2 , 0
                          289.86         1863.54
Permanent Ineff=
       F       F
Bank Sta=197.7,220.4
XS Rating Curve= 0 ,0
Exp/Cntr=0.3,0.1

Type RM Length L Ch R = 1 ,1091    ,112.5,111.2,109.1
XS GIS Cut Line= 3
2215289.65278246690508.6660969472215328.74842442690373.786132205
2215463.62838916690222.290519633
#Sta/Elev= 30
       0 1900.43     3.6 1898.08     7.8 1896.74      12 1896.19    24.5 1896.49
    41.1 1895.88    53.6 1894.56    57.8 1892.41    66.1 1886.01    95.3 1865.88
    99.4 1862.18   103.6 1857.51   105.91855.974   107.7 1854.82   112.8 1854.62
   120.2 1854.85   124.3 1855.58     134  1857.2   162.7 1856.68   178.7 1857.78
   200.2 1857.38   223.8 1857.96   248.4 1856.68   267.9 1856.99   270.8 1857.58
   284.9 1863.36   307.3 1869.62   323.3 1870.78   333.1 1876.21   343.3 1878.99
#Mann= 3 ,-1,0
       0      .1       0   105.9    .045       0   124.3      .1       0
Bank Sta=105.9,124.3
XS Rating Curve= 0 ,0
Exp/Cntr(USF)=0,0
Exp/Cntr=0.3,0.1

Type RM Length L Ch R = 1 ,980     ,170,169.6,162.3
XS GIS Cut Line= 3
2215406.96061281690558.2887856142215433.19046152  690397.7056579
 2215548.1569154690214.700536401
#Sta/Elev= 30
       0 1900.13       9 1897.03    17.3 1890.39    21.4 1889.42    37.6 1889.58
    41.7 1887.86    53.8 1877.36    74.1 1863.29    86.2 1856.98    94.3 1855.95
   126.8 1856.49   134.9 1854.46     143 1853.09   151.8 1854.78   155.1 1855.95
   162.3 1856.57   182.7 1854.59   196.4 1854.86   205.8 1857.56   214.6 1858.46
   228.5 1857.93   240.7 1856.35   257.8 1856.18   281.4 1866.06   295.6 1866.32
   298.7 1867.28     305 1872.05   309.8 1874.13   328.7 1879.48   378.8 1897.09
#Mann= 4 ,-1,0
       0      .1       0   134.9    .045       0   151.8      .1       0
  272.71     .06       0
#XS Ineff= 2 , 0
                          214.31         1861.53
Permanent Ineff=
       F       F
Bank Sta=134.9,151.8
XS Rating Curve= 0 ,0
Exp/Cntr=0.3,0.1

Type RM Length L Ch R = 1 ,810     ,154.6,164.3,168.5
XS GIS Cut Line= 4
2215514.24161563690597.4052398142215514.10809162690589.304314275
2215533.93446905690401.6598937632215605.95004812690256.659934128
#Sta/Elev= 30
       0  1894.5    12.3 1891.09    20.3 1887.98    24.3 1884.46    28.3 1879.86
    32.4 1878.08    48.5 1878.56    52.5 1877.22    65.8 1865.89    76.6 1858.37
    80.6 1856.46    88.7 1854.33   101.11853.821   108.8 1852.03   116.8 1851.56
   120.9 1851.79   124.51853.176   128.9 1854.56   161.1 1854.17   177.2 1852.79
   189.2 1856.84   201.8 1857.84   228.8 1855.13   259.9 1856.19   270.4 1860.91
   282.2 1861.88   285.4 1862.81   294.3 1870.04   297.3 1871.49   358.7 1893.41
#Mann= 4 ,-1,0
       0      .1       0   101.1    .045       0   124.5      .1       0
   297.3     .06       0
#XS Ineff= 2 , 0
                          184.79         1858.42
Permanent Ineff=
       F       F
Bank Sta=101.1,124.5
XS Rating Curve= 0 ,0
Exp/Cntr=0.3,0.1