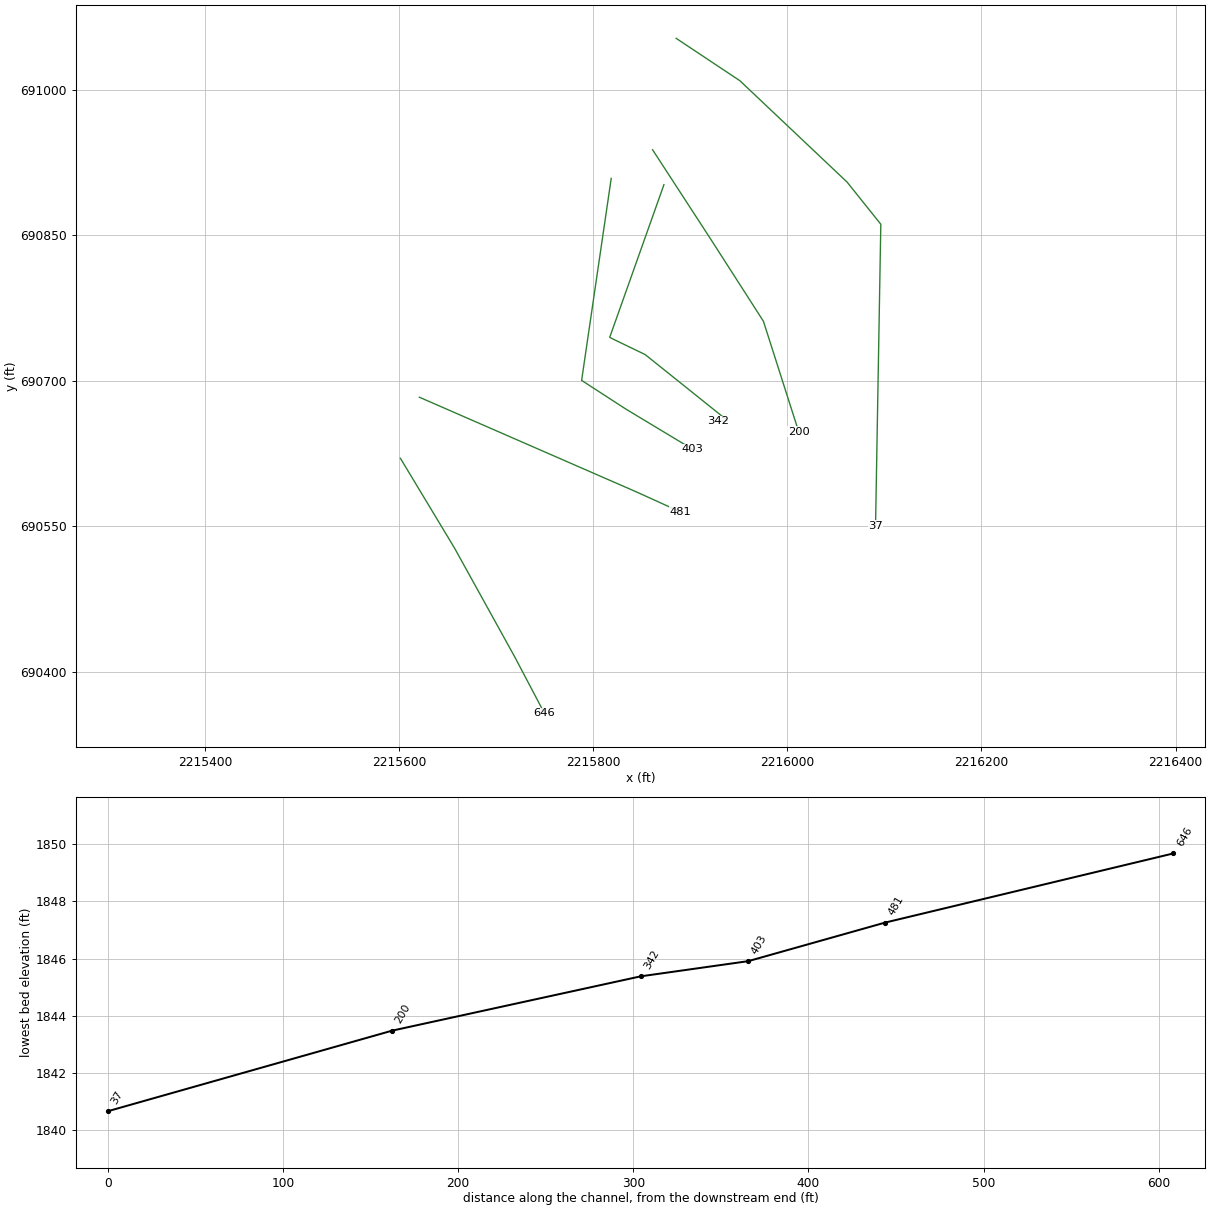
HEC-RAS study LAURELRN4.prj: LAURELRN4

--- LAURELRN4.g01 (geometry) --- (continued)

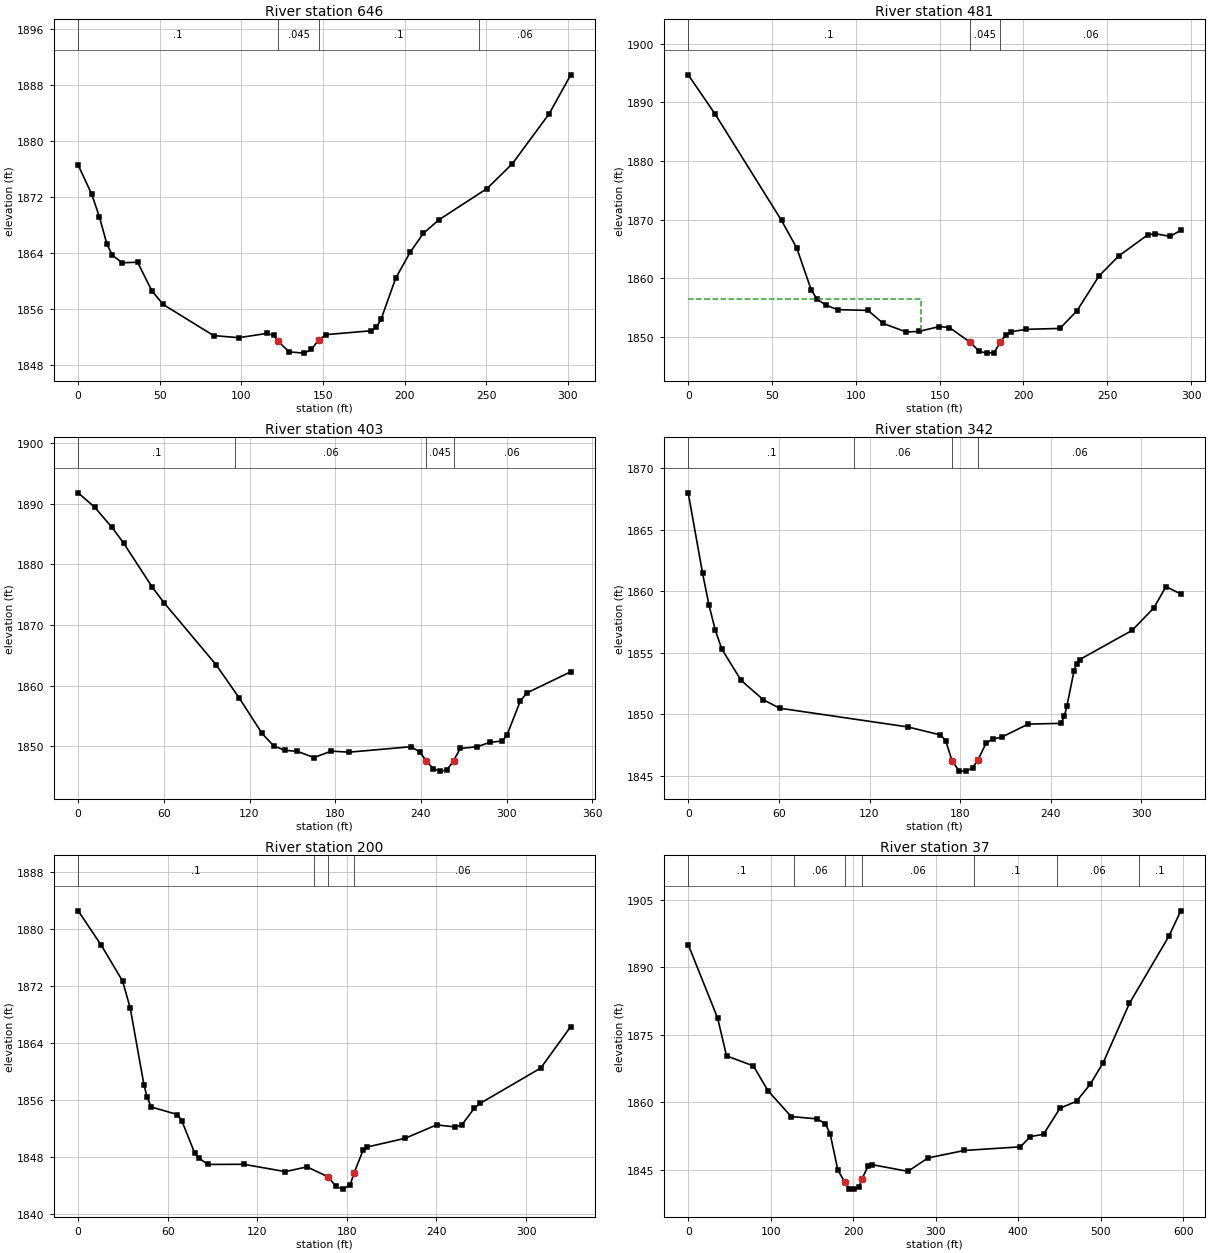
Type RM Length L Ch R = 1 ,646     ,154,164.6,173.9
XS GIS Cut Line= 4
2215601.32715808690620.2761903572215657.16818869690527.651126063
2215718.91975515690416.0232943742215749.79553839690357.438474906
#Sta/Elev= 30
       0 1876.59     8.3 1872.43      13 1869.19    17.6 1865.29      21 1863.68
      27 1862.61    36.4 1862.69    45.1 1858.63      52 1856.66      83 1852.19
    98.5 1851.89   115.6  1852.5   120.1 1852.21   122.6 1851.35   129.3 1849.86
   138.4 1849.68     143  1850.2   147.4 1851.59   152.1 1852.33   179.5 1852.88
   182.8 1853.36   185.8 1854.63   194.6  1860.4   203.4 1864.09   211.5 1866.81
   221.1 1868.76   250.6 1873.24   266.1 1876.79   288.7 1883.95   301.9 1889.51
#Mann= 4 ,-1,0
       0      .1       0   122.6    .045       0   147.4      .1       0
  245.73     .06       0
Bank Sta=122.6,147.4
XS Rating Curve= 0 ,0
Exp/Cntr(USF)=0,0
Exp/Cntr=0.3,0.1

Type RM Length L Ch R = 1 ,481     ,80.3,78.2,75.4
XS GIS Cut Line= 3
2215620.88952047690683.183074069 2215844.6201959690585.568097848
2215889.95236729690564.991680794
#Sta/Elev= 30
       0 1894.68    16.2 1887.94    55.7 1869.86    64.8 1865.15    73.4 1858.04
    76.9 1856.45    82.1 1855.45    89.1 1854.67   107.3 1854.54   116.4 1852.31
   130.1 1850.86   137.7 1850.96   149.9 1851.79   155.9 1851.61   168.1 1849.14
   173.8 1847.54   178.2 1847.26   182.5 1847.33   186.3 1849.15   189.4 1850.31
   192.4 1850.89   201.5 1851.31   221.8 1851.47   231.9 1854.44     245 1860.36
   256.8  1863.8   274.3 1867.44   278.8  1867.6   287.5 1867.15   293.9 1868.19
#Mann= 3 ,-1,0
       0      .1       0   168.1    .045       0   186.3     .06       0
#XS Ineff= 2 , 0
          138.76 1856.43
Permanent Ineff=
       F       F
Bank Sta=168.1,186.3
XS Rating Curve= 0 ,0
Exp/Cntr(USF)=0,0
Exp/Cntr=0.3,0.1

Type RM Length L Ch R = 1 ,403     ,59.1,61.3,63.1
XS GIS Cut Line= 4
2215818.54494357 690908.645617812215788.05254231690700.529103295
2215833.56804586690671.0039563952215902.44077556690629.530107842
#Sta/Elev= 30
       0 1891.76    11.6 1889.38    23.7 1886.06    31.8 1883.49      52 1876.18
    60.1 1873.66    96.5 1863.46   112.7    1858   128.8 1852.11   136.9 1850.08
     145 1849.32   153.2 1849.19   165.2 1848.15   177.3 1849.21   189.5 1849.03
   233.1 1849.93   239.1 1849.08   243.9 1847.59   248.6 1846.32   253.3 1845.91
   258.2 1846.09   262.9 1847.62   267.6 1849.64   279.5 1849.93   288.2 1850.65
     297 1850.87   300.3 1851.84   309.7 1857.48   314.3  1858.8     345 1862.28
#Mann= 4 ,-1,0
       0      .1       0     110     .06       0   243.9    .045       0
   262.9     .06       0
Bank Sta=243.9,262.9
XS Rating Curve= 0 ,0
Exp/Cntr(USF)=0,0
Exp/Cntr=0.3,0.1

Type RM Length L Ch R = 1 ,342     ,148,141.9,132.9
XS GIS Cut Line= 6
2215872.85319078690902.1586315632215817.01405586690744.915736252
 2215820.1177629690743.2543782162215853.51322031690727.126227528
 2215938.3623132690659.1738615692215928.58102855690658.510320719
#Sta/Elev= 30
       0 1867.98     9.5 1861.46    13.8 1858.84      18  1856.8    22.3 1855.28
      35 1852.75    49.8 1851.17    60.5 1850.49   145.3 1848.97   166.9 1848.32
   170.4 1847.86   174.6 1846.23   179.3 1845.39   183.8 1845.38   188.2 1845.64
   191.8  1846.3   197.1 1847.64   201.5 1847.99   207.5 1848.14     225  1849.2
   246.8 1849.26     249 1849.88   250.6 1850.64   255.4 1853.55     257 1854.11
   259.1 1854.44   293.8 1856.81   308.2 1858.64   316.2 1860.37     326 1859.76
#Mann= 4 ,-1,0
       0      .1       0     110     .06       0   174.6    .045       0
   191.8     .06       0
Bank Sta=174.6,191.8
XS Rating Curve= 0 ,0
Exp/Cntr(USF)=0,0
Exp/Cntr=0.3,0.1

Type RM Length L Ch R = 1 ,200     ,160.5,162.4,163.5
XS GIS Cut Line= 4
2215861.16874406 690938.138822282215919.94115327 690847.77454885
2215975.35922574690761.4806931492216011.77681622690647.477801213
#Sta/Elev= 30
       0  1882.6    15.5 1877.76    29.8 1872.71    34.9  1868.9    44.1  1858.1
    46.2 1856.44    48.9 1855.03    66.5 1853.96    69.4  1853.1      78 1848.58
    80.9 1847.82      87 1846.95   110.9 1846.97   138.8 1845.94   153.3 1846.61
   167.4 1845.21   172.7 1843.86   177.4 1843.48   182.2 1844.09   184.81845.737
   190.9 1848.96   193.8 1849.41   219.1 1850.63   240.1 1852.51   252.5 1852.22
   256.9 1852.47   265.3 1854.83   269.5 1855.56   309.9  1860.5     330 1866.33
#Mann= 4 ,-1,0
       0      .1       0   157.8     .06       0   167.4    .045       0
   184.8     .06       0
Bank Sta=167.4,184.8
XS Rating Curve= 0 ,0
Exp/Cntr(USF)=0,0
Exp/Cntr=0.3,0.1

Type RM Length L Ch R = 1 ,37      ,,,
XS GIS Cut Line= 5
 2215885.4606461691052.9524523772215951.07087595691009.320549708
2216061.57009583690904.8302066542216096.32177756690861.390604484
2216090.89182729690550.797448967
#Sta/Elev= 30
       0 1895.01    35.7 1878.67    46.5 1870.27      79 1868.05    96.8 1862.51
   124.9 1856.79   156.1 1856.27   166.3 1855.22   172.1 1852.92   181.5 1844.84
     190 1842.16   195.4 1840.79   201.3 1840.66   206.9 1841.11   210.41842.841
   217.9 1845.69   223.4 1846.08   266.3 1844.61   290.7 1847.59   334.7 1849.25
   402.7 1850.06   414.7 1852.33   430.7 1852.85   450.7 1858.64   470.7 1860.19
   487.4 1863.99   503.1 1868.79   534.9 1881.96   582.8 1896.91   597.1 1902.51
#Mann= 7 ,-1,0
       0      .1       0  128.79     .06       0     190    .045       0
   210.4     .06       0   346.5      .1       0   446.5     .06       0
   546.5      .1       0
Bank Sta=190,210.4
XS Rating Curve= 0 ,0
Exp/Cntr(USF)=0,0
Exp/Cntr=0.3,0.1
LCMann Table=0

Chan Stop Cuts=-1
Use User Specified Reach Order=0
Composite Channel Slope=5